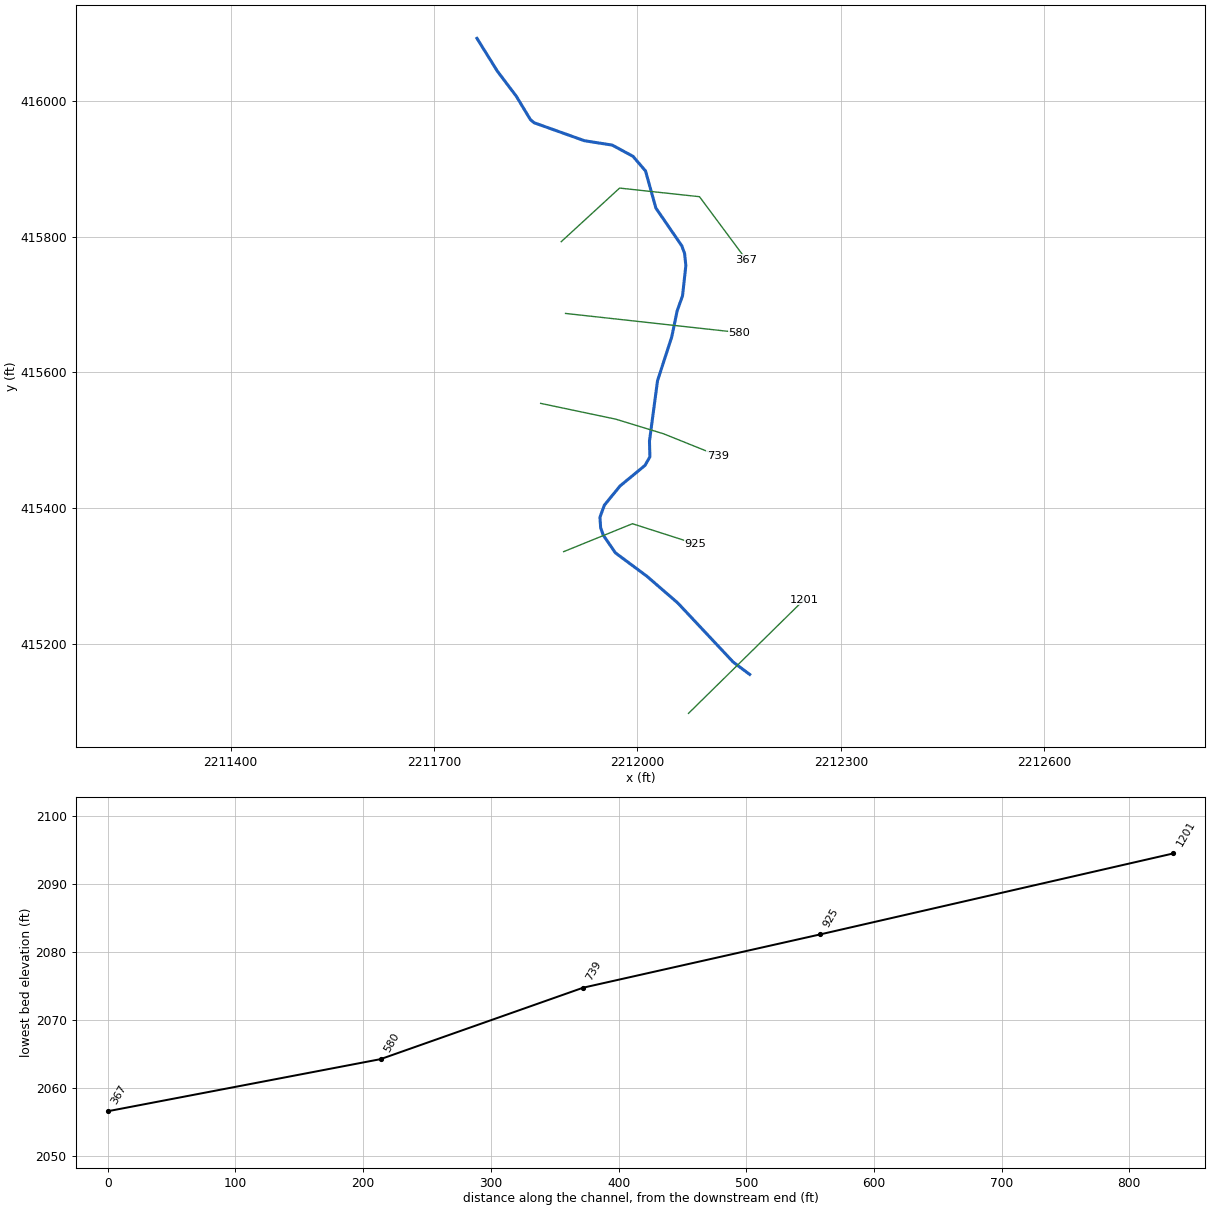
--- CHKNHSRN.prj (project) ---

Proj Title=CHKNHSRN
Current Plan=p01
Default Exp/Contr=0,0
English Units
Geom File=g01
Flow File=f01
Plan File=p01
Background Map Layer=Inundation Boundary (01pct Value_0)
BEGIN DESCRIPTION:
----------MODEL BY WOOD PLC 2021----------
Stream Name: Chicken House Run
Flood Zone: Enhanced Approximate
Pocahontas County, WV
HEC-RAS Version: RAS 6.1
Vertical Datum: NAVD88
Projection: NAD 1983 StatePlane West Virginia S FIPS 4702 (US Feet)
Terrain: 1-meter LIDAR (FEMA Region III 3DEP collected 2016-2018)
Land Use: 2019 NLCD
Hydrologic Method:
WV SIR2010-5033 regression equations
Model Notes:
Normal depth tie in with Greenbrier River
END DESCRIPTION:
DSS Export Rating Curves= 0
DSS Export Rating Curve Sorted= 0
DSS Export Volume Flow Curves= 0
DXF OffsetX= 0
DXF OffsetY= 0
DXF ScaleX= 0
DXF ScaleY= 0

--- CHKNHSRN.p01 (plan) ---

Plan Title=Floodplain
Program Version=6.10
Short Identifier=Floodplain
Geom File=g01
Flow File=f01
Subcritical Flow
K Sum by GR= 0
Std Step Tol= 0.01
Critical Tol= 0.01
Num of Std Step Trials= 20
Max Error Tol= 0.3
Flow Tol Ratio= 0.001
Split Flow NTrial= 30
Split Flow Tol= 0.02
Split Flow Ratio= 0.02
Log Output Level= 0
Friction Slope Method= 1
Unsteady Friction Slope Method= 2
Unsteady Bridges Friction Slope Method= 1
Parabolic Critical Depth
Global Vel Dist= 0 , 0 , 0
Global Log Level= 0
CheckData=True
Encroach Param=-1 ,0,0, 0
Mapping Interval=1HOUR
Computation Time Step Use Courant=        0
Computation Time Step Use Time Series=    0
Computation Time Step Count To Double=0
Computation Time Step Max Doubling=0
Computation Time Step Max Halving=0
Computation Time Step Residence Courant=0
Run HTab= 0
Run UNet= 0
Run Sediment= 0
Run PostProcess= 0
Run WQNet= 0
Run RASMapper=-1
UNET Theta= 0
UNET Theta Warmup= 0
UNET ZTol= 0
UNET ZSATol= 0
UNET MxIter= 0
UNET Max Iter WO Improvement= 0
UNET MaxInSteps= 0
UNET DtIC= 0
UNET DtMin= 0
UNET MaxCRTS= 0
UNET WFStab= 0
UNET SFStab= 0
UNET WFX= 1
UNET SFX= 1
UNET Gravity=32.174
UNET 1D Methodology=Finite Difference
UNET DSS MLevel= 1
UNET Pardiso=0
UNET DZMax Abort= 0
UNET Use Existing IB Tables= 0
UNET Froude Reduction=False
UNET Froude Limit= 0
UNET Froude Power= 0
UNET D1 Cores= 0
UNET WindReference=Eulerian
UNET WindDragFormulation=Hsu (1988)
UNET D2 Coriolis=0
UNET D2 Cores= 0
UNET D2 Theta= 1
UNET D2 Theta Warmup= 1
UNET D2 Z Tol= 0.01
UNET D2 Volume Tol= 0.01
UNET D2 Max Iterations= 20
UNET D2 Equation= 0
UNET D2 RampUpFraction=0.1
UNET D2 TimeSlices= 1
UNET D2 Turbulence Formulation=Non-Conservative (original)
UNET D2 Eddy Viscosity=0.3
UNET D2 Transverse Eddy Viscosity=0.1
UNET D2 Smagorinsky Mixing=0
UNET D2 BCVolumeCheck=0
UNET D2 Cores=0
UNET D2 SolverType=PARDISO (Direct)
UNET D2 Minimum Iterations= 2147483647
UNET D2 Maximum Iterations= 2147483647
UNET D2 Restart Number= 10
UNET D2 Relaxation Coeff=1.3
UNET D2 SOR Precondition Iterations= 10
UNET D2 ILUT Maximum Fill= 8
UNET D2 ILUT Tolerance=1E-08
UNET D1D2 MaxIter= 0
UNET D1D2 ZTol=0.01
UNET D1D2 QTol=0.1
UNET D1D2 MinQTol=1
Write IC File= 0
Write IC File at Fixed DateTime=0
Write IC File at Sim End=0
Echo Input=False
Echo Parameters=False
Echo Output=False
Write Detailed= 0
HDF Write Warmup=0
HDF Write Time Slices=0
HDF Flush=0
HDF Compression= 1
HDF Chunk Size= 1
HDF Spatial Parts= 1
HDF Use Max Rows=0
HDF Fixed Rows= 1
Calibration Method= 0
Calibration Iterations= 20
Calibration Max Change=0.05
Calibration Tolerance=0.2
Calibration Maximum=1.5
Calibration Minimum=0.5
Calibration Optimization Method= 1
WQ AD Non Conservative
WQ ULTIMATE=-1
WQ Max Comp Step=1HOUR
WQ Output Interval=15MIN
WQ Output Selected Increments= 0
WQ Output face flow=0
WQ Output face velocity=0
WQ Output face area=0
WQ Output face dispersion=0
WQ Output cell volume=0
WQ Output cell surface area=0
WQ Output cell continuity=0
WQ Output cumulative cell continuity=0
WQ Output face conc=0
WQ Output face dconc_dx=0
WQ Output face courant=0
WQ Output face peclet=0
WQ Output face adv mass=0
WQ Output face disp mass=0
WQ Output cell mass=0
WQ Output cell source sink temp=0
WQ Output nsm pathways=0
WQ Output nsm derived pathways=0
WQ Create Restart=0
WQ Fixed Restart=0
WQ System Summary=0
WQ Write To DSS=0
Sorting and Armoring Iterations= 10
XS Update Threshold= 0.02
Bed Roughness Predictor= 0
Hydraulics Update Threshold= 0.02
Energy Slope Method= 1
Volume Change Method= 1
Sediment Retention Method= 0
Sediment TS Multiplier= 1
Warm Up Method= 0
XS Weighting Method= 0
Number of US Weighted Cross Sections= 1
Number of DS Weighted Cross Sections= 1
Upstream XS Weight=0
Main XS Weight=1
Downstream XS Weight=0
Number of DS XS's Weighted with US Boundary= 1
Upstream Boundary Weight= 1
Weight of XSs Associated with US Boundary= 0
Number of US XS's Weighted with DS Boundary= 1
Downstream Boundary Weight= 0.5
Weight of XSs Associated with DS Boundary= 0.5
Percentile Method= 0
Sediment Output Level= 3
Mass or Volume Output= 0
Output Increment Type= 1
Profile and TS Output Increment= 1
Transport Output Increment 1
XS Output Flag= 0
XS Output Increment= 10
Read HDF5 Sediment Hotstart= 0
Sediment Hotstart Type= 0
Write Gradation File= 0
Read Gradation Hotstart= 0
Write HDF5 File= 1
Write Binary Output= 1
Write DSS Sediment File= 0
DSS Sediment Output Type= 1
SV Curve= 0
Specific Gage Flag= 0
Subcell Erosion Methods= 0
Subcell Deposition Methods= 0
Advection Scheme= 1
Matrix Solver= 0
Implicit Weighting Factor= 1
Maximum Outer Loop Convergence Iterations= 5
Convergence Maximum Absolute= 0.001
Convergence RMSE= 0.0001
Grain Fractions Max Abs Error= 0.001
Max Subgrid Regions= 1
Max Subgrid Length Scale= 3.402823E+38
Initial Layer Thickness= 3.402823E+38
Min Layer Thickness= 3.402823E+38
Max Layer Thickness= 3.402823E+38
Number of Layers= 5

--- CHKNHSRN.f01 (steady flow) ---

Flow Title=Flow
Program Version=4.00
Number of Profiles=6
Profile Names=01pct,10pct,04pct,02pct,0_2pct,01plus
River Rch & RM=CHKNHSRN,Main,1201
     582     308     409     493     812     861
Boundary for River Rch & Prof#=CHKNHSRN,Main      ,1
Up Type=0
Dn Type=3
Dn Slope=0.047435
Boundary for River Rch & Prof#=CHKNHSRN,Main      ,2
Up Type=0
Dn Type=3
Dn Slope=0.047435
Boundary for River Rch & Prof#=CHKNHSRN,Main      ,3
Up Type=0
Dn Type=3
Dn Slope=0.047435
Boundary for River Rch & Prof#=CHKNHSRN,Main      ,4
Up Type=0
Dn Type=3
Dn Slope=0.047435
Boundary for River Rch & Prof#=CHKNHSRN,Main      ,5
Up Type=0
Dn Type=3
Dn Slope=0.047435
Boundary for River Rch & Prof#=CHKNHSRN,Main      ,6
Up Type=0
Dn Type=3
Dn Slope=0.047435

--- CHKNHSRN.g01 (geometry) ---

Geom Title=Geometry
Program Version=6.10

River Reach=CHKNHSRN        ,Main
Reach XY= 30
     2212165.629      415154.484     2212141.354      415172.667
     2212059.477      415259.942     2212013.971      415299.333
     2211967.437      415333.908     2211949.609         415360.
     2211945.774      415370.768     2211944.728       415386.35
       2211951.2      415404.108      2211974.32      415432.425
     2212011.196      415462.826     2212018.372      415475.426
     2212017.795      415498.694     2212029.659      415587.716
     2212050.662      415652.447     2212058.572      415690.607
     2212066.566      415713.078     2212071.428      415757.544
     2212069.638      415775.256     2212065.499      415786.669
     2212027.215      415842.482     2212011.963      415897.176
     2211993.447      415918.776     2211962.835      415935.308
     2211921.788      415941.773     2211847.651      415968.258
     2211842.144      415972.875     2211821.564      416007.064
     2211793.468      416044.267     2211763.295      416092.798

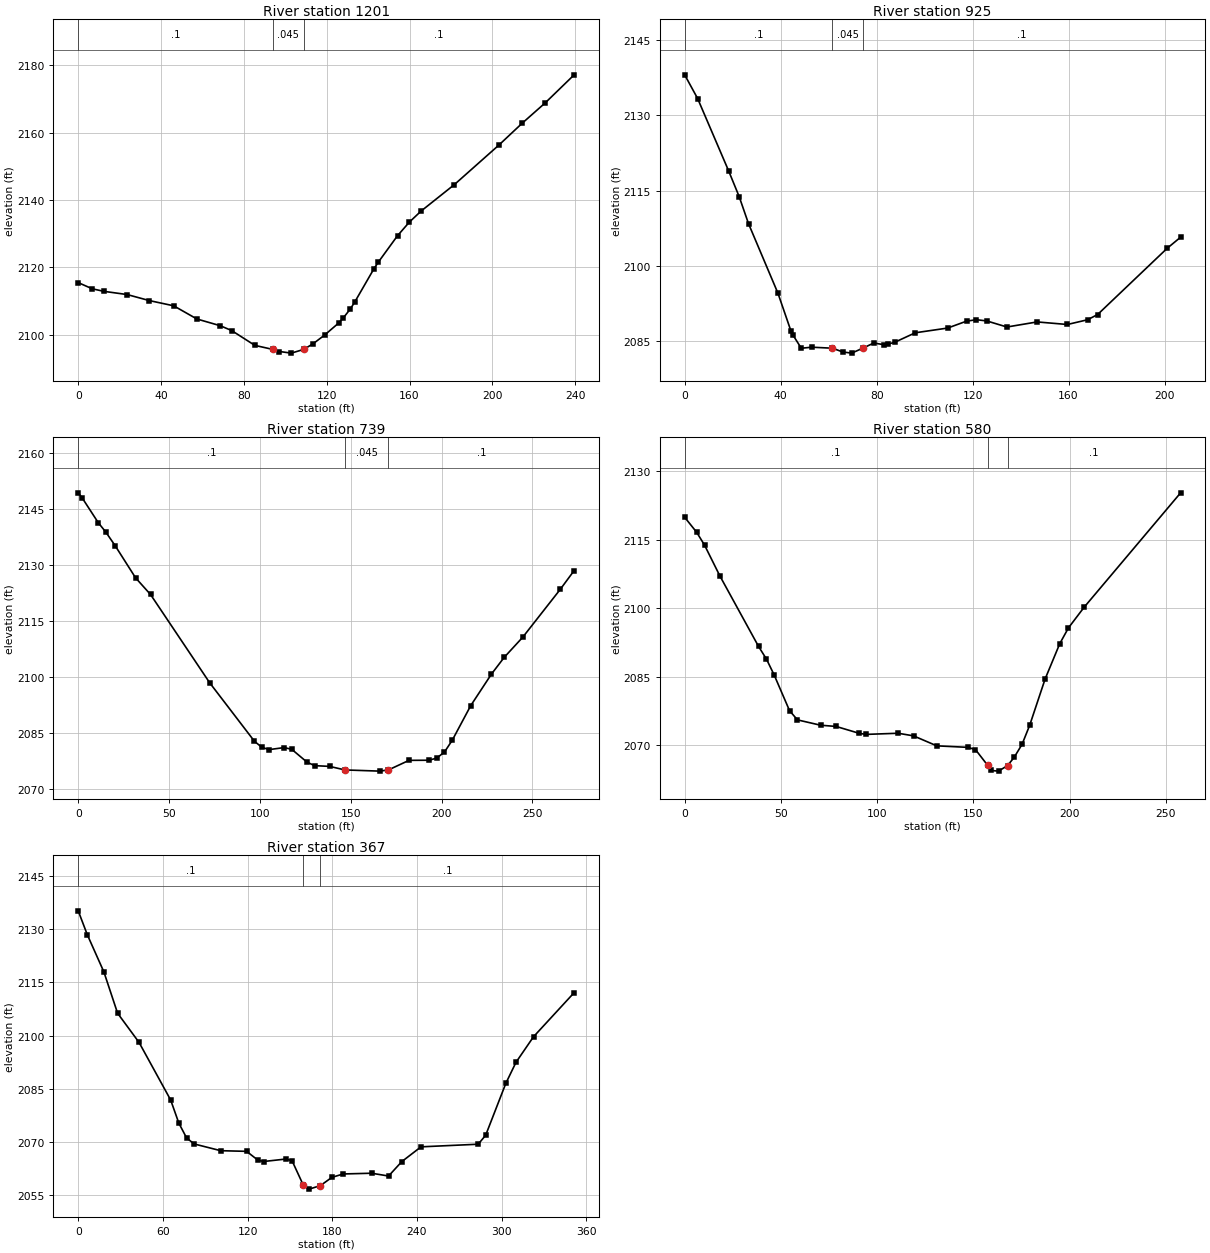
Type RM Length L Ch R = 1 ,1201    ,276.6,276.6,276.6
XS GIS Cut Line= 2
2212075.33453364415097.0442147432212246.11290901415264.999807055
#Sta/Elev= 30
       0 2115.47     6.8 2113.63    12.4 2112.88    23.6 2111.93    34.4 2110.13
    46.1 2108.59    57.3 2104.68    68.5  2102.7    74.1 2101.25    85.3 2096.85
      94 2095.65    97.2 2095.03   102.9 2094.55  108.822095.636   113.4 2097.32
     119 2099.91   125.7 2103.44     128 2104.99   131.4 2107.64   133.6 2109.77
   142.8 2119.57   144.9 2121.52   154.2 2129.38   159.9 2133.41   165.6  2136.7
   181.7 2144.57   203.1 2156.24   214.4 2162.75   225.6 2168.83   239.5 2177.11
#Mann= 3 ,-1,0
       0      .1       0      94    .045       0  108.82      .1       0
Bank Sta=94,108.82
XS Rating Curve= 0 ,0
Exp/Cntr(USF)=0,0
Exp/Cntr=0.3,0.1

Type RM Length L Ch R = 1 ,925     ,185.7,185.7,185.7
XS GIS Cut Line= 3
2211891.14793871415335.5693836572211992.67183889415376.803793129
2212085.11798423415347.164570956
#Sta/Elev= 30
       0 2138.04     5.4 2133.32    18.4 2118.83    22.7 2113.81    26.6 2108.42
    38.9 2094.53    44.3 2087.03      45 2086.34    48.6 2083.61    52.9 2083.82
    61.6 2083.62    65.9 2082.87    69.6 2082.64    74.5 2083.68    78.8 2084.65
    83.1 2084.32    84.9 2084.46    87.5 2084.79    96.1 2086.69   109.6 2087.63
   117.5 2089.01   121.6 2089.29   125.9 2089.05   134.3 2087.84   146.9 2088.85
   159.5 2088.34   167.9 2089.28   172.1 2090.32   201.1 2103.51   206.7 2105.72
#Mann= 3 ,0,0
       0      .1       0    61.6    .045       0    74.5      .1       0
Bank Sta=61.6,74.5
XS Rating Curve= 0 ,0
Exp/Cntr(USF)=0,0
Exp/Cntr=0.3,0.1

Type RM Length L Ch R = 1 ,739     ,158.7,158.7,158.7
XS GIS Cut Line= 4
2211857.27454194415554.335071121 2211968.0687772415531.047110843
2212038.54206368 415509.474597142212118.38197537415477.414232625
#Sta/Elev= 30
       0 2149.43     2.3 2147.98    11.1 2141.38    15.2  2138.9    20.3 2135.28
    31.6 2126.62    39.8 2122.17    72.4 2098.47      97 2082.81   101.1 2081.18
   105.1 2080.57   113.3 2081.11   117.5 2080.67   125.9 2077.23   130.1 2076.27
   138.4 2076.07   146.8 2075.12     166  2074.8   170.8 2075.13   182.1 2077.69
     193 2077.72   197.3 2078.28   201.6 2079.91   205.9 2083.08   216.1 2092.39
   227.5 2100.84   234.5 2105.31   244.7 2110.71   265.3 2123.51     273 2128.59
#Mann= 3 ,0,0
       0      .1       0   146.8    .045       0   170.8      .1       0
Bank Sta=146.8,170.8
XS Rating Curve= 0 ,0
Exp/Cntr(USF)=0,0
Exp/Cntr=0.3,0.1

Type RM Length L Ch R = 1 ,580     ,213.6,213.6,213.6
XS GIS Cut Line= 2
2211893.97072177415687.0058751322212150.13828484415658.778044492
#Sta/Elev= 30
       0 2119.91     6.2 2116.64    10.3 2113.83    18.3 2107.05    38.4  2091.6
    42.5 2088.83    46.5 2085.36    54.5 2077.53    58.6 2075.52    70.6 2074.35
    78.7 2074.08    90.8 2072.56    94.3 2072.34   110.9 2072.59   118.9 2072.02
     131 2069.83   147.1  2069.5   151.1 2069.01  157.45 2065.55   159.2 2064.43
   163.1 2064.29   167.8 2065.52   171.2 2067.31   175.3 2070.15   179.3 2074.37
   187.3 2084.49   194.9 2092.22   199.4 2095.67   207.5 2100.17   257.7 2125.27
#Mann= 3 ,0,0
       0      .1       0  157.45    .045       0   167.8      .1       0
Bank Sta=157.45,167.8
XS Rating Curve= 0 ,0
Exp/Cntr(USF)=0,0
Exp/Cntr=0.3,0.1

Type RM Length L Ch R = 1 ,367     ,,,
XS GIS Cut Line= 4
2211887.61945988415792.8602400352211973.71434333415871.898165829
2212091.56553626415859.1956420412212160.72372133415766.043800927
#Sta/Elev= 30
       0 2135.21     6.4  2128.5    18.2 2117.95    27.9  2106.3    43.1 2098.06
    65.5  2081.8    71.3 2075.26    76.8 2071.08    82.2 2069.38     101 2067.48
   119.3  2067.3   127.4 2064.79   131.4 2064.43     147 2065.12   151.5 2064.66
   159.6 2057.66   163.6 2056.63   171.6 2057.62   179.7 2059.94   187.7 2060.91
   207.9 2061.12   219.9 2060.33   229.3 2064.41   242.9 2068.57   283.4 2069.31
   288.7 2071.84     303 2086.51   310.2 2092.44   322.6 2099.65   351.4 2112.11
#Mann= 3 ,0,0
       0      .1       0   159.6    .045       0   171.6      .1       0
Bank Sta=159.6,171.6
XS Rating Curve= 0 ,0
Exp/Cntr(USF)=0,0
Exp/Cntr=0.3,0.1
LCMann Table=0

Chan Stop Cuts=-1
Use User Specified Reach Order=0
Composite Channel Slope=5